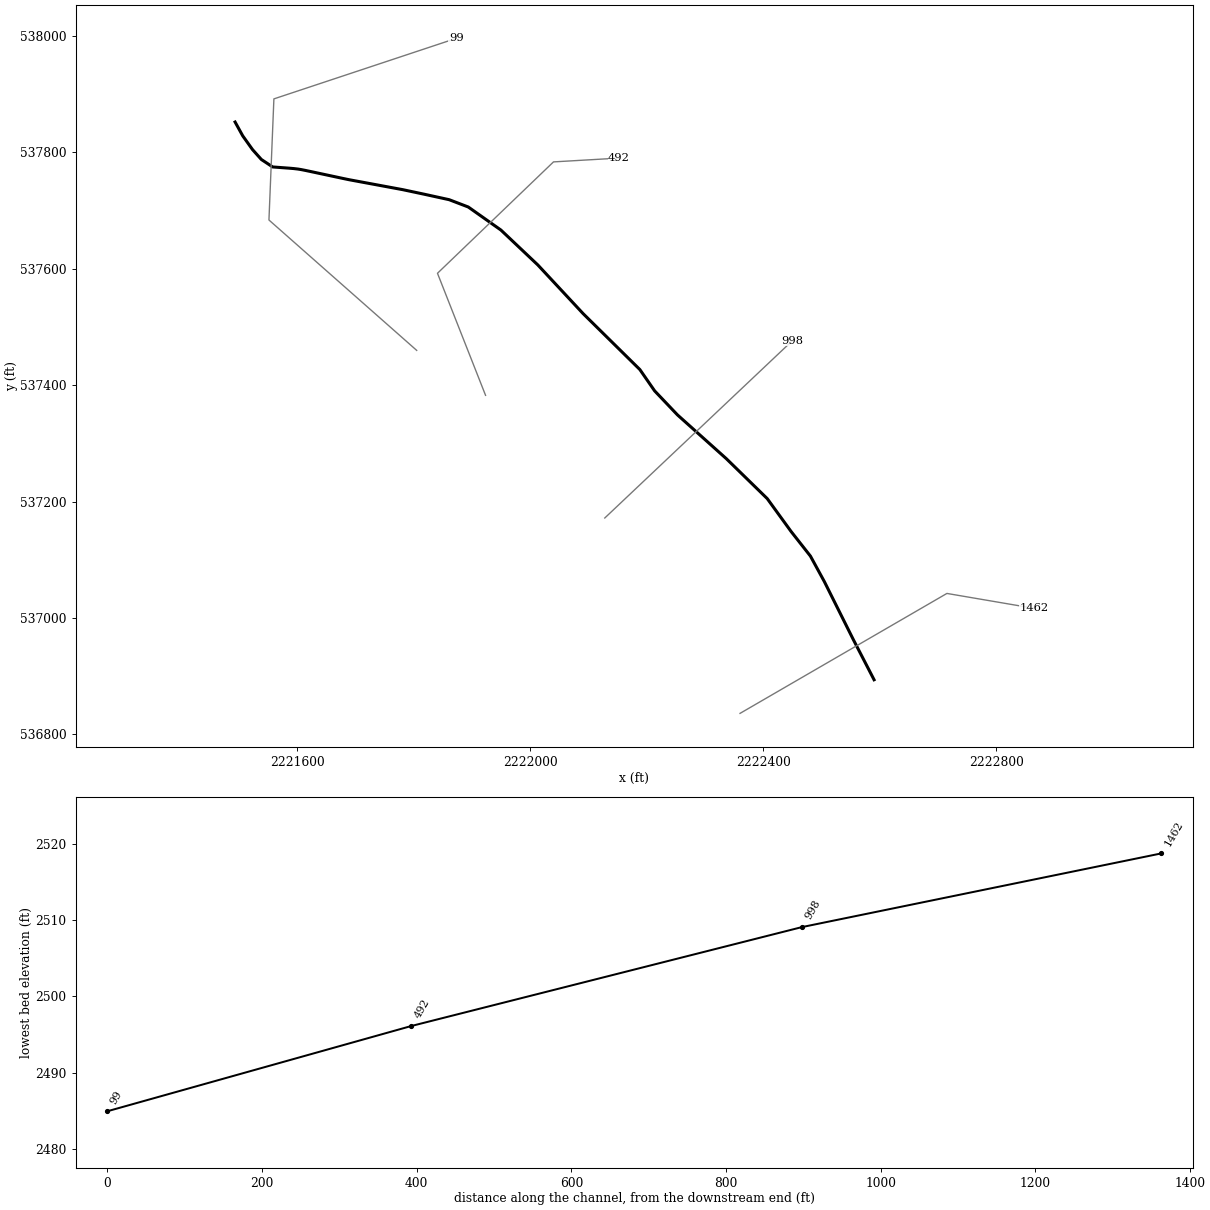
--- DRYFK.prj (project) ---

Proj Title=DRYFK
Current Plan=p01
Default Exp/Contr=0,0
English Units
Geom File=g01
Flow File=f01
Plan File=p01
BEGIN DESCRIPTION:
----------MODEL BY WOOD PLC 2022----------
AFH study
Randolph County, WV
HEC-RAS Version: RAS 6.2
Vertical Datum: NAVD88
Projection: NAD 1983 StatePlane West Virginia S FIPS 4702 (US Feet)
Terrain: 1-meter LIDAR (FEMA Region III 3DEP collected 2016-2018)
Land Use: 2019 NLCD
Hydrologic Method:
WV SIR2010-5033 regression equations
Additional Model Notes:
4 Shared XS from Dry Fork model in Pocahontas County upstream.
END DESCRIPTION:
DSS Export Rating Curves= 0
DSS Export Rating Curve Sorted= 0
DSS Export Volume Flow Curves= 0
DXF OffsetX= 0
DXF OffsetY= 0
DXF ScaleX= 0
DXF ScaleY= 0

--- DRYFK.p01 (plan) ---

Plan Title=Floodplain
Program Version=6.20
Short Identifier=Floodplain
Geom File=g01
Flow File=f01
Subcritical Flow
K Sum by GR= 0
Std Step Tol= 0.01
Critical Tol= 0.01
Num of Std Step Trials= 20
Max Error Tol= 0.3
Flow Tol Ratio= 0.001
Split Flow NTrial= 30
Split Flow Tol= 0.02
Split Flow Ratio= 0.02
Log Output Level= 0
Friction Slope Method= 1
Unsteady Friction Slope Method= 2
Unsteady Bridges Friction Slope Method= 1
Parabolic Critical Depth
Global Vel Dist= 0 , 0 , 0
Global Log Level= 0
CheckData=True
Encroach Param=-1 ,0,0, 0
Mapping Interval=1HOUR
Computation Time Step Use Courant=        0
Computation Time Step Use Time Series=    0
Computation Time Step Count To Double=0
Computation Time Step Max Doubling=0
Computation Time Step Max Halving=0
Computation Time Step Residence Courant=0
Run HTab= 0
Run UNet= 0
Run Sediment= 0
Run PostProcess= 0
Run WQNet= 0
Run RASMapper=-1
UNET Theta= 0
UNET Theta Warmup= 0
UNET ZTol= 0
UNET ZSATol= 0
UNET MxIter= 0
UNET Max Iter WO Improvement= 0
UNET MaxInSteps= 0
UNET DtIC= 0
UNET DtMin= 0
UNET MaxCRTS= 0
UNET WFStab= 0
UNET SFStab= 0
UNET WFX= 1
UNET SFX= 1
UNET Gravity=32.174
UNET 1D Methodology=Finite Difference
UNET DSS MLevel= 1
UNET Pardiso=0
UNET DZMax Abort= 0
UNET Use Existing IB Tables= 0
UNET Froude Reduction=False
UNET Froude Limit= 0
UNET Froude Power= 0
UNET D1 Cores= 0
UNET WindReference=Eulerian
UNET WindDragFormulation=Hsu (1988)
UNET D2 Coriolis=0
UNET D2 Cores= 0
UNET D2 Theta= 1
UNET D2 Theta Warmup= 1
UNET D2 Z Tol= 0.01
UNET D2 Volume Tol= 0.01
UNET D2 Max Iterations= 20
UNET D2 Equation= 0
UNET D2 RampUpFraction=0.1
UNET D2 TimeSlices= 1
UNET D2 Turbulence Formulation=Non-Conservative (original)
UNET D2 Eddy Viscosity=0.3
UNET D2 Transverse Eddy Viscosity=0.1
UNET D2 Smagorinsky Mixing=0
UNET D2 BCVolumeCheck=0
UNET D2 Cores=0
UNET D2 SolverType=PARDISO (Direct)
UNET D2 Minimum Iterations= 2147483647
UNET D2 Maximum Iterations= 2147483647
UNET D2 Restart Number= 10
UNET D2 Relaxation Coeff=1.3
UNET D2 SOR Precondition Iterations= 10
UNET D2 ILUT Maximum Fill= 8
UNET D2 ILUT Tolerance=1E-08
UNET D1D2 MaxIter= 0
UNET D1D2 ZTol=0.01
UNET D1D2 QTol=0.1
UNET D1D2 MinQTol=1
Write IC File= 0
Write IC File at Fixed DateTime=0
Write IC File at Sim End=0
Echo Input=False
Echo Parameters=False
Echo Output=False
Write Detailed= 0
HDF Write Warmup=0
HDF Write Time Slices=0
HDF Flush=0
HDF Compression= 1
HDF Chunk Size= 1
HDF Spatial Parts= 1
HDF Use Max Rows=0
HDF Fixed Rows= 1
Calibration Method= 0
Calibration Iterations= 20
Calibration Max Change=0.05
Calibration Tolerance=0.2
Calibration Maximum=1.5
Calibration Minimum=0.5
Calibration Optimization Method= 1
WQ AD Non Conservative
WQ ULTIMATE=-1
WQ Max Comp Step=1HOUR
WQ Output Interval=15MIN
WQ Output Selected Increments= 0
WQ Output face flow=0
WQ Output face velocity=0
WQ Output face area=0
WQ Output face dispersion=0
WQ Output cell volume=0
WQ Output cell surface area=0
WQ Output cell continuity=0
WQ Output cumulative cell continuity=0
WQ Output face conc=0
WQ Output face dconc_dx=0
WQ Output face courant=0
WQ Output face peclet=0
WQ Output face adv mass=0
WQ Output face disp mass=0
WQ Output cell mass=0
WQ Output cell source sink temp=0
WQ Output nsm pathways=0
WQ Output nsm derived pathways=0
WQ Create Restart=0
WQ Fixed Restart=0
WQ System Summary=0
WQ Write To DSS=0
Sorting and Armoring Iterations= 10
XS Update Threshold= 0.02
Bed Roughness Predictor= 0
Hydraulics Update Threshold= 0.02
Energy Slope Method= 1
Volume Change Method= 1
Sediment Retention Method= 0
Sediment TS Multiplier= 1
Warm Up Method= 0
XS Weighting Method= 0
Number of US Weighted Cross Sections= 1
Number of DS Weighted Cross Sections= 1
Upstream XS Weight=0
Main XS Weight=1
Downstream XS Weight=0
Number of DS XS's Weighted with US Boundary= 1
Upstream Boundary Weight= 1
Weight of XSs Associated with US Boundary= 0
Number of US XS's Weighted with DS Boundary= 1
Downstream Boundary Weight= 0.5
Weight of XSs Associated with DS Boundary= 0.5
Percentile Method= 0
Sediment Output Level= 3
Mass or Volume Output= 0
Output Increment Type= 1
Profile and TS Output Increment= 1
Transport Output Increment 1
XS Output Flag= 0
XS Output Increment= 10
Read HDF5 Sediment Hotstart= 0
Sediment Hotstart Type= 0
Write Gradation File= 0
Read Gradation Hotstart= 0
Write HDF5 File= 1
Write Binary Output= 1
Write DSS Sediment File= 0
DSS Sediment Output Type= 1
SV Curve= 0
Specific Gage Flag= 0
Subcell Erosion Methods= 0
Subcell Deposition Methods= 0
Advection Scheme= 1
Matrix Solver= 0
Implicit Weighting Factor= 1
Maximum Outer Loop Convergence Iterations= 5
Convergence Maximum Absolute= 0.001
Convergence RMSE= 0.0001
Grain Fractions Max Abs Error= 0.001
Max Subgrid Regions= 1
Max Subgrid Length Scale= 3.402823E+38
Initial Layer Thickness= 3.402823E+38
Min Layer Thickness= 3.402823E+38
Max Layer Thickness= 3.402823E+38
Number of Layers= 5

--- DRYFK.f01 (steady flow) ---

Flow Title=Flow
Program Version=6.20
Number of Profiles= 1
Profile Names=P100yr
River Rch & RM=DRYFK,Main            ,1462
    1880
Boundary for River Rch & Prof#=DRYFK,Main            , 1
Up Type= 0
Dn Type= 3
Dn Slope=0.02852
DSS Import GetInterval= 0
DSS Import GetPeak= 0
DSS Import FillOption= 0

--- DRYFK.g01 (geometry) ---

Geom Title=Geometry
Program Version=6.20

River Reach=DRYFK           ,Main
Reach XY= 30
2222590.42189339536893.779176827  2222554.746801536962.865440652
2222505.05583845537062.4152395582222481.10010308537106.296444565
2222448.08671051537148.3198648542222406.93019186537205.052527547
2222336.67836386 537273.651143612222252.78942399537348.862279296
2222213.53097236537390.1866717042222188.16287747537426.805657595
 2222090.6793474537522.9320704342222012.88771926537606.567765281
2221949.55158302537666.488577187 2221893.4594804537706.101440594
2221860.69527371537718.6588655412221818.34177776537727.952716291
2221780.94693336537735.9059014922221688.62707151537753.030855075
2221678.90300953537755.0469271392221623.05108714537767.002939984
2221613.33293071537769.0521484912221606.02913955537770.477014393
2221601.13807324537771.2801623942221593.80409838 537772.13711606
2221586.43993989537772.7801593992221557.52824328537774.929620677
2221538.10948726537787.7369143422221522.95065413537804.704211602
     2221506.083      537828.3872221492.97694083537852.142738807

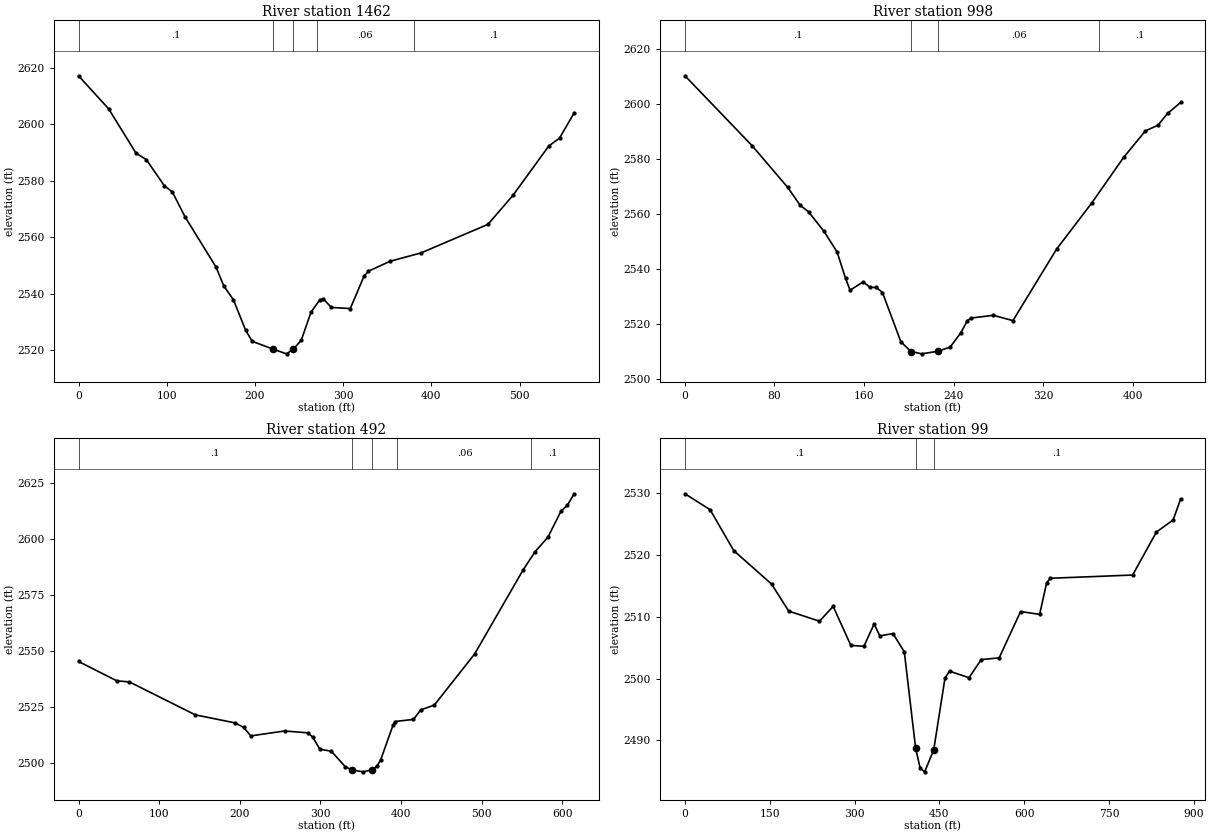
Type RM Length L Ch R = 1 ,1462    ,464.7,464.7,464.7
XS GIS Cut Line= 3
2222360.21521984536836.0301900082222715.52334101537042.117315308
2222864.48541312537016.678056496
#Sta/Elev= 30
       0 2617.08    34.2 2605.38    65.2 2589.71    76.9 2587.42    97.4 2578.14
   106.3 2576.06   120.8 2567.16   155.9 2549.44   164.7 2542.76   175.7 2537.81
   189.5 2527.04   196.9 2523.17   220.3 2520.43   235.8 2518.74   243.7 2520.46
   252.5 2523.52   263.5  2533.4   273.4  2537.8   277.4 2538.19   286.7 2535.15
   308.1 2534.76   323.6 2546.16   328.6 2547.95   353.1 2551.47   388.4 2554.44
   464.2 2564.54   492.6 2574.83   533.1 2592.23   545.3 2595.04   561.9 2603.96
#Mann= 5 ,-1,0
       0      .1       0   220.3    .045       0   243.7      .1       0
     270     .06       0     380      .1       0
Bank Sta=220.3,243.7
XS Rating Curve= 0 ,0
Exp/Cntr=0.3,0.1

Type RM Length L Ch R = 1 ,998     ,505.2,505.2,505.2
XS GIS Cut Line= 2
2222127.93543953537171.7572022952222449.81003099537476.154440371
#Sta/Elev= 30
       0  2610.2    60.3 2584.63    91.7 2569.67     103 2563.08   110.4 2560.75
   124.3 2553.61     136 2546.09   143.5 2536.52   147.6 2532.22   159.3 2535.25
   165.3 2533.25     171 2533.24   176.5 2531.38     193 2513.42   202.1 2509.91
   211.6 2509.08   226.1 2510.03   237.1 2511.55   246.6  2516.8   252.4 2521.14
   255.8 2522.11   275.7 2523.09   293.1 2521.15   332.2 2547.21   363.4 2563.85
   392.1 2580.54   411.5 2590.15   422.8 2592.24   431.3 2596.49     443  2600.5
#Mann= 4 ,-1,0
       0      .1       0   202.1    .045       0   226.1     .06       0
     370      .1       0
Bank Sta=202.1,226.1
XS Rating Curve= 0 ,0
Exp/Cntr=0.3,0.1

Type RM Length L Ch R = 1 ,492     ,393.2,393.2,393.2
XS GIS Cut Line= 4
2221923.15911573537382.504955164  2221840.578621537592.233195752
2222039.82044956537783.6102152882222152.54937887537790.164222807
#Sta/Elev= 30
       0 2545.31    47.5 2536.69    63.1  2536.2   144.7 2521.53   193.7 2517.96
   204.9 2515.92   213.5 2512.13   255.6 2514.33   284.5 2513.49   290.3 2511.63
   299.3  2506.2   313.5  2505.3   330.7 2498.43   338.9 2496.94   353.1 2496.11
   364.4  2497.1   370.1 2498.72   374.6  2501.4   389.9 2516.83   392.7 2518.55
   415.3 2519.49   424.5 2523.75   441.1 2525.85   491.1 2548.62   551.4  2586.2
   566.1  2594.2   582.2 2600.81   598.2 2612.29   606.2    2615   614.6 2620.08
#Mann= 5 ,-1,0
       0      .1       0   338.9    .045       0   364.4      .1       0
   395.4     .06       0  561.67      .1       0
Bank Sta=338.9,364.4
XS Rating Curve= 0 ,0
Exp/Cntr=0.3,0.1

Type RM Length L Ch R = 1 ,99      ,,,
XS GIS Cut Line= 4
2221804.88549605 537459.737379762221551.12743296537683.766464753
 2221559.6214267537891.8693114772221872.83744601537995.920734839
#Sta/Elev= 30
       0 2529.89    44.5 2527.31    86.3  2520.7   153.3 2515.28   183.5 2510.92
   237.9 2509.29   262.1 2511.68   293.4 2505.38   316.5 2505.22   334.6 2508.84
   344.7 2506.91   367.9 2507.29     388 2504.33     408 2488.76     416 2485.54
     424 2484.93     440 2488.47     460 2500.12     468 2501.21   502.4 2500.15
   524.1 2503.08   555.8 2503.36   593.7 2510.85   627.4 2510.39   639.7 2515.49
   646.3 2516.23   791.9 2516.75     834 2523.71   863.5 2525.65   876.8 2529.04
#Mann= 3 ,-1,0
       0      .1       0     408    .045       0     440      .1       0
Bank Sta=408,440
XS Rating Curve= 0 ,0
Exp/Cntr=0.3,0.1
LCMann Table=0

Chan Stop Cuts=-1
Use User Specified Reach Order=0
Composite Channel Slope=5